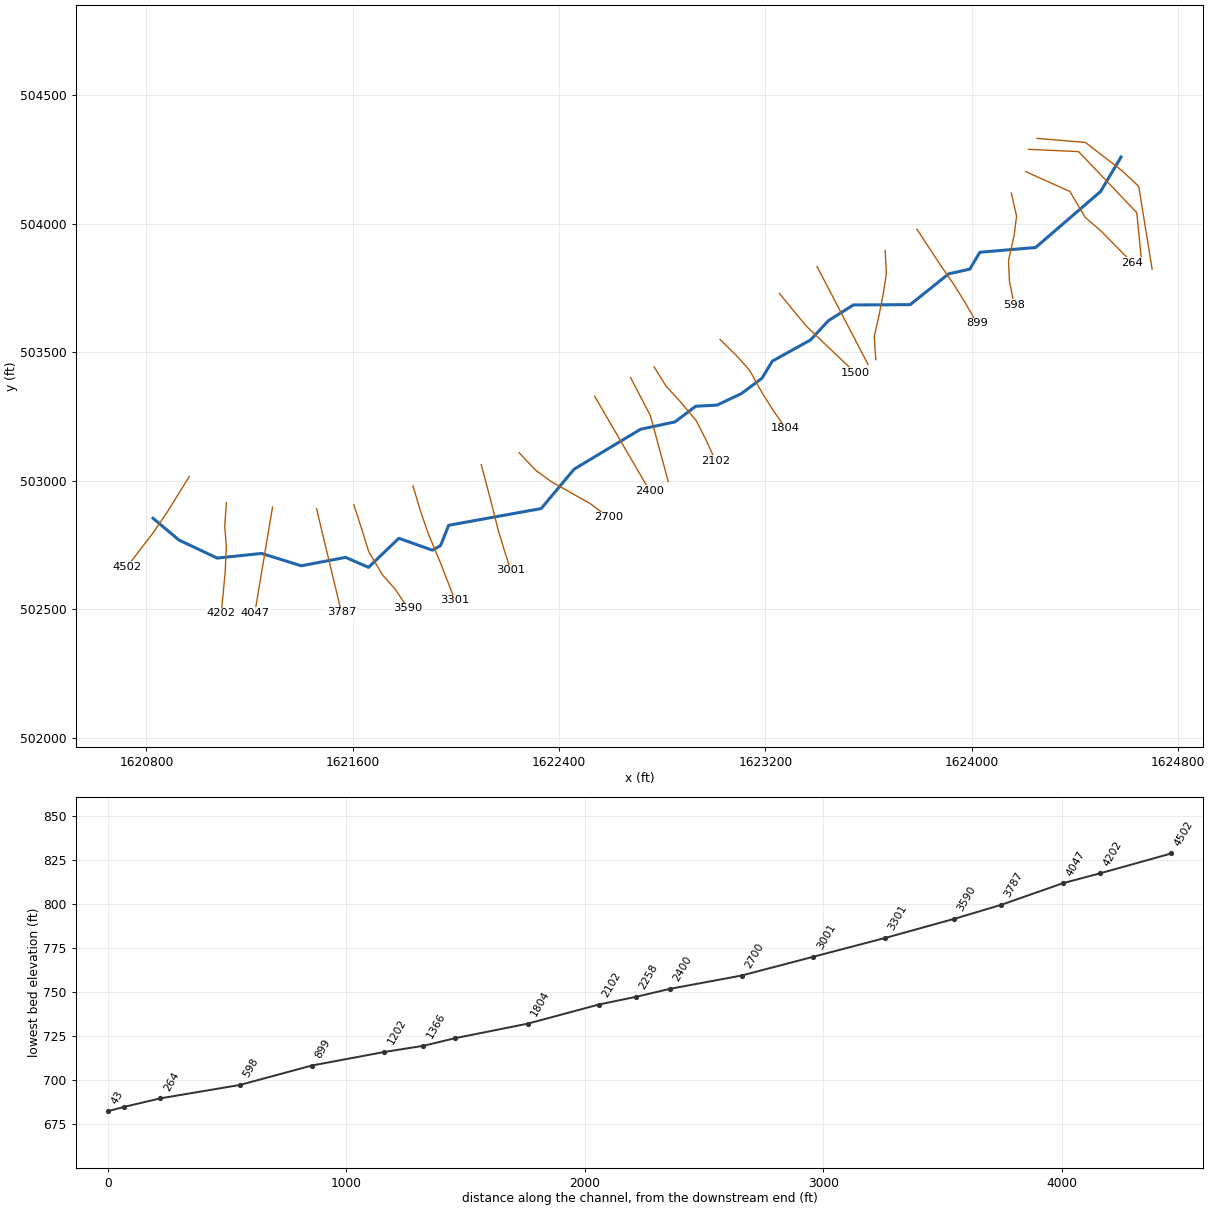
--- GraveCkT1.prj (project) ---

Proj Title=GraveCkT1
Current Plan=p01
Default Exp/Contr=0,0
English Units
Geom File=g01
Flow File=f01
Plan File=p01
BEGIN DESCRIPTION:
---------- MODELED AS PART OF WVEM CTP PROGRAM, 2025----------
Stream Name: Grave Creek Tributary 1
Flood Zone: AFH
Marshall County, WV
HEC-RAS Version: RAS 6.6
Vertical Datum: NAVD88
Projection: NAD 1983 StatePlane West Virginia N FIPS 4701 (US Feet)
Terrain: 1-meter West Virginia FEMA R3 South Central (collected 2018-2019)
Land Use: 2024 NLCD
Hydrologic Method:
Duda et al., "Estimation of magnitude and frequency of floods for rural, unregulated streams in and near Virginia and West Virginia." September 8, 2025.
Additional Model Notes:
None
END DESCRIPTION:
DSS Export Rating Curves= 0
DSS Export Rating Curve Sorted= 0
DSS Export Volume Flow Curves= 0
DXF OffsetX= 0
DXF OffsetY= 0
DXF ScaleX= 0
DXF ScaleY= 0

--- GraveCkT1.p01 (plan) ---

Plan Title=Floodplain
Program Version=6.60
Short Identifier=Floodplain
Geom File=g01
Flow File=f01
Subcritical Flow
K Sum by GR= 0
Std Step Tol= 0.01
Critical Tol= 0.01
Num of Std Step Trials= 20
Max Error Tol= 0.3
Flow Tol Ratio= 0.001
Split Flow NTrial= 30
Split Flow Tol= 0.02
Split Flow Ratio= 0.02
Log Output Level= 0
Friction Slope Method= 1
Unsteady Friction Slope Method= 2
Unsteady Bridges Friction Slope Method= 1
Parabolic Critical Depth
Global Vel Dist= 0 , 0 , 0
Global Log Level= 0
CheckData=False
Encroach Param=-1 ,0,0, 0
Flow Ratio Tolerance=0.1
Flow Ratio Min Ratio=0.5
Flow Ratio Max Ratio=4
Flow Ratio Max Iterations= 10
Mapping Interval=1HOUR
Computation Time Step Use Courant=        0
Computation Time Step Use Time Series=    0
Computation Time Step Count To Double=0
Computation Time Step Max Doubling=0
Computation Time Step Max Halving=0
Computation Time Step Residence Courant=0
Run HTab= 0
Run UNet= 0
Run Sediment= 0
Run PostProcess= 0
Run WQNet= 0
Run RASMapper=-1
UNET Theta= 0
UNET Theta Warmup= 0
UNET ZTol= 0
UNET ZSATol= 0
UNET MxIter= 0
UNET Max Iter WO Improvement= 0
UNET MaxInSteps= 0
UNET DtIC= 0
UNET DtMin= 0
UNET MaxCRTS= 0
UNET WFStab= 0
UNET SFStab= 0
UNET WFX= 1
UNET SFX= 1
UNET Gravity=32.17405
UNET 1D Methodology=Finite Difference
UNET DSS MLevel= 1
UNET Pardiso=0
UNET DZMax Abort= 0
UNET Use Existing IB Tables= 0
UNET Froude Reduction=False
UNET Froude Limit= 0
UNET Froude Power= 0
UNET D1 Cores= 0
UNET WindReference=Eulerian
UNET WindDragFormulation=Hsu (1988)
UNET D2 Coriolis=0
UNET D2 Cores= 0
UNET D2 Theta= 1
UNET D2 Theta Warmup= 1
UNET D2 Z Tol= 0.01
UNET D2 Volume Tol= 0.01
UNET D2 Max Iterations= 20
UNET D2 Advanced Convergence=0
UNET D2 WS Max Tol=0.15
UNET D2 WS RMS Tol=0.002
UNET D2 WS Stall Tol=1
UNET D2 Equation= 0
UNET D2 RampUpFraction=0.1
UNET D2 TimeSlices= 1
UNET D2 Turbulence Formulation=Non-Conservative (original)
UNET D2 Eddy Viscosity=0.3
UNET D2 Transverse Eddy Viscosity=0.1
UNET D2 Smagorinsky Mixing=0
UNET D2 BCVolumeCheck=0
UNET D2 Cores=0
UNET D2 SolverType=PARDISO (Direct)
UNET D2 Minimum Iterations= 3
UNET D2 Maximum Iterations= 30
UNET D2 Restart Number= 10
UNET D2 Relaxation Coeff=1.3
UNET D2 SOR Precondition Iterations= 10
UNET D2 ILUT Maximum Fill= 8
UNET D2 ILUT Tolerance=1E-08
UNET D2 Convergence Tolerance=0.00001
PS Theta= 1
PS WS Tol= 0.01
PS Volume Tol= 0.01
PS Max Iterations= 20
PS Equation= 0
PS Advance Time Step=-1
PS Target Courant=0.9
PS Time Slices= 1
PS Iterate With 2D=0
PS Project Initial WSE from DS=-1
PS Ramp Up Initial WSE from US=-1
PS Cores=0
UNET D1D2 MaxIter= 0
UNET D1D2 ZTol=0.01
UNET D1D2 QTol=0.1
UNET D1D2 MinQTol=1
Write IC File= 0
Write IC File at Fixed DateTime=0
Write IC File at Sim End=0
Echo Input=False
Echo Parameters=False
Echo Output=False
Write Detailed= 0
HDF Write Warmup=0
HDF Write Time Slices=0
HDF Flush=0
HDF Compression= 1
HDF Chunk Size= 1
HDF Spatial Parts= 1
HDF Use Max Rows=0
HDF Fixed Rows= 1
Calibration Method= 0
Calibration Iterations= 20
Calibration Max Change=0.05
Calibration Tolerance=0.2
Calibration Maximum=1.5
Calibration Minimum=0.5
Calibration Optimization Method= 1
WQ AD Non Conservative
WQ ULTIMATE=-1
WQ Max Comp Step=1HOUR
WQ Output Interval=15MIN
WQ Output Selected Increments= 0
WQ Create Restart=0
WQ Fixed Restart=0
WQ System Summary=0
WQ Write To DSS=0
Sorting and Armoring Iterations= 10
XS Update Threshold= 0.02
Bed Roughness Predictor= 0
Processes Affected by Predictor=Sediment Only
Hydraulics Update Threshold= 0.02
Energy Slope Method= 1
Volume Change Method= 1
Sediment Retention Method= 0
Sediment TS Multiplier= 1
Warm Up Method= 0
XS Weighting Method= 0
Number of US Weighted Cross Sections= 1
Number of DS Weighted Cross Sections= 1
Upstream XS Weight=0
Main XS Weight=1
Downstream XS Weight=0
Number of DS XS's Weighted with US Boundary= 1
Upstream Boundary Weight= 1
Weight of XSs Associated with US Boundary= 0
Number of US XS's Weighted with DS Boundary= 1
Downstream Boundary Weight= 0.5
Weight of XSs Associated with DS Boundary= 0.5
Percentile Method= 0
Sediment Output Level= 3
Mass or Volume Output= 0
Output Increment Type= 1
Profile and TS Output Increment= 1
Transport Output Increment 1
XS Output Flag= 0
XS Output Increment= 10
Read HDF5 Sediment Hotstart= 0
Sediment Hotstart Type= 0
Write Gradation File= 0
Read Gradation Hotstart= 0
Write HDF5 File= 1
Write Binary Output= 1
Write DSS Sediment File= 0
DSS Sediment Output Type= 1
SV Curve= 0
Specific Gage Flag= 0
Subcell Erosion Methods= 0
Subcell Deposition Methods= 0
Advection Scheme= 1
Matrix Solver= 0
Implicit Weighting Factor= 1
Maximum Outer Loop Convergence Iterations= 5
Convergence Maximum Absolute= 0.001
Convergence RMSE= 0.0001
Grain Fractions Max Abs Error= 0.001
Max Subgrid Regions= 1
Max Subgrid Length Scale= 3.402823E+38
Initial Layer Thickness= 3
Min Layer Thickness= 0.1
Max Layer Thickness= 6
Number of Layers= 5

--- GraveCkT1.f01 (steady flow) ---

Flow Title=Flow
Program Version=6.60
Number of Profiles= 1
Profile Names=P100yr
River Rch & RM=GraveCkT1,Main,4502
     777
Boundary for River Rch & Prof#=GraveCkT1,Main            , 1
Up Type= 0
Dn Type= 3
Dn Slope=0.031085
DSS Import GetInterval= 0
DSS Import GetPeak= 0
DSS Import FillOption= 0

--- GraveCkT1.g01 (geometry) ---

Geom Title=Geometry
Program Version=6.60

River Reach=GraveCkT1       ,Main
Reach XY= 30
     1620825.505      502853.459     1620925.978      502768.811
     1621074.096       502698.75     1621246.582      502716.646
     1621400.029       502668.67     1621572.134      502701.415
     1621660.852      502662.578     1621778.508      502775.664
     1621908.729      502729.211     1621940.332      502747.488
     1621971.555      502826.306     1622330.413      502891.401
     1622457.775      503044.438     1622715.597      503199.911
     1622849.139      503228.666     1622929.312      503289.589
      1623012.41      503293.975     1623106.611      503338.814
     1623186.191      503398.213     1623226.932      503465.227
     1623374.668      503547.472     1623444.348      503622.863
     1623540.681      503683.785     1623761.143      503684.928
     1623910.646       503804.99     1623992.038      503823.023
     1624031.272      503888.819     1624247.424      503907.339
     1624499.443      504125.471     1624578.614      504259.486

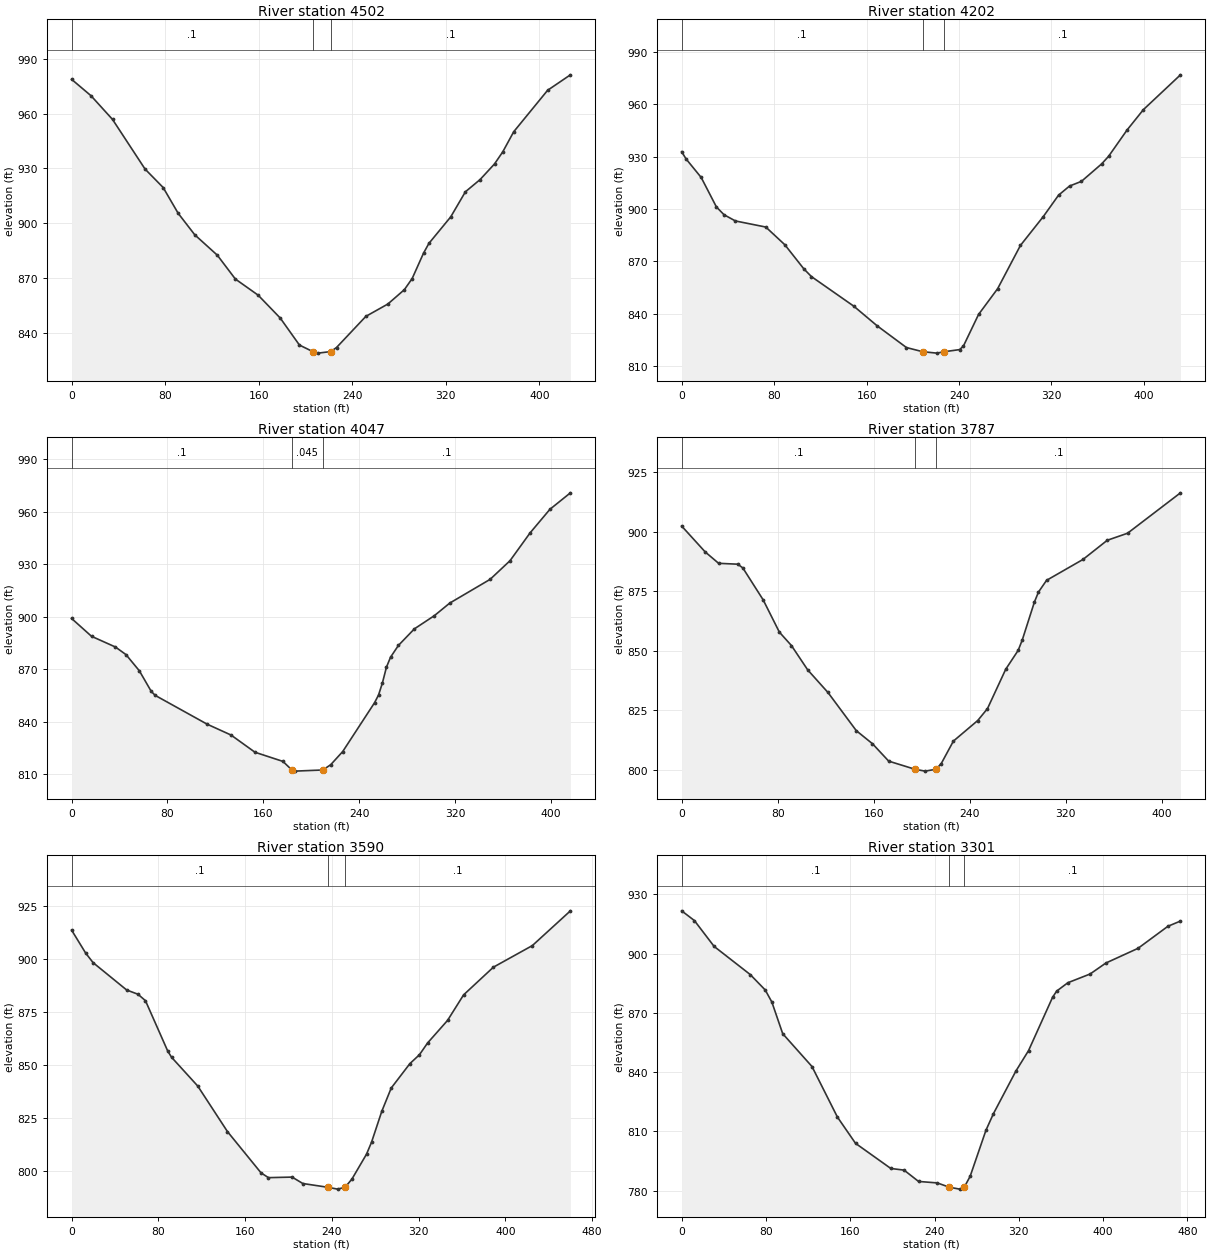
Type RM Length L Ch R = 1 ,4502    ,293.7,299.6,303.7
XS GIS Cut Line= 6
1620966.13818508503016.3505641671620920.13565242502941.919610679
1620880.70430084502878.1218380031620824.58761518502795.247003749
1620778.40069968502735.3337377611620724.66097775 502665.25973092
#Sta/Elev= 30
       0  978.82    16.6  969.83      35  956.84    62.8  929.66    78.3  919.53
    91.1  905.44   105.3  893.65   124.6  882.47     140  869.42   159.5  860.57
   178.4  848.03   194.8  833.24  206.22829.6649   210.7  828.82  221.48829.6633
   226.5  831.89   251.6  848.96   270.4  855.72   284.5  863.57   291.2   869.7
   300.9  883.59   305.5  888.94   324.2  903.51   336.7  917.21   349.2  923.87
   361.6  932.47   368.7  939.15     378  950.09     407  972.82   426.5  981.29
#Mann= 3 ,-1,0
       0      .1       0  206.22    .045       0  221.48      .1       0
Bank Sta=206.22,221.48
XS Rating Curve= 0 ,0
Exp/Cntr(USF)=0,0
Exp/Cntr=0.3,0.1

Type RM Length L Ch R = 1 ,4202    ,153.5,155,149.1
XS GIS Cut Line= 6
1621109.68054892502914.1762278381621103.50109933  502822.4349415
1621109.62871176502745.647365421 1621105.2025395502645.625255749
1621098.22387892 502570.950536341621090.08216292502483.830303758
#Sta/Elev= 30
       0  932.85     3.8  928.73    16.9  918.09    30.1  901.18    36.7  896.73
    46.5  893.19    72.8   889.7    89.3  879.54   105.7  865.76   112.3  861.32
     149  844.35     169  833.21   194.5  820.69  208.54818.3012   220.8  817.49
  227.27818.3011   240.5  819.51   243.8  821.56   256.9  839.65   273.4   854.4
   293.1  879.15   312.9  895.69   326.1  907.95   335.6  913.18   345.9  915.86
   363.4  925.87   369.4  930.21   385.4  945.29   399.5  956.93   431.6  976.88
#Mann= 3 ,-1,0
       0      .1       0  208.54    .045       0  227.27      .1       0
Bank Sta=208.54,227.27
XS Rating Curve= 0 ,0
Exp/Cntr(USF)=0,0
Exp/Cntr=0.3,0.1

Type RM Length L Ch R = 1 ,4047    ,256,260.2,263.5
XS GIS Cut Line= 2
1621288.76837429502897.257445825 1621220.3492169502486.680453742
#Sta/Elev= 30
       0  899.15    16.6  888.97    36.6  882.83    45.4  878.48    56.5  869.27
    66.5  857.43    69.8  855.18   113.1  838.74     133  832.55     153  822.71
   176.3  817.48  183.83812.5706   186.2  811.92  209.58812.5714   216.2  815.59
   226.2   823.1   252.8  851.03   256.1  855.42   259.3  862.24   262.7  871.32
   266.1     877   272.7  883.76     286  893.21   302.7  900.76   315.5  907.93
   349.2   921.5   365.8  932.15   382.5  948.01   399.1  961.53   416.2  970.94
#Mann= 3 ,-1,0
       0      .1       0  183.83    .045       0  209.58      .1       0
Bank Sta=183.83,209.58
XS Rating Curve= 0 ,0
Exp/Cntr(USF)=0,0
Exp/Cntr=0.3,0.1

Type RM Length L Ch R = 1 ,3787    ,193.5,196.9,197.6
XS GIS Cut Line= 2
1621459.34001641502891.1122030011621556.03447337502486.885751333
#Sta/Elev= 30
       0  902.35    19.6   891.5    30.8  886.72    46.8  886.35      51  884.76
    67.9   871.4    81.4  857.87    91.5  852.21     105  842.04   121.9  832.55
   145.5  816.54     159  811.05   172.5  803.76  194.37800.3555   202.8  799.57
  211.96800.3549   216.3  802.76   226.4  812.16   246.7   820.8   254.8  825.79
     270  842.29   280.4  850.23   283.8  854.59   293.9  870.48   297.3  874.67
     304  879.57   334.4  888.35   354.6  896.38   371.5  899.33   415.6  916.28
#Mann= 3 ,-1,0
       0      .1       0  194.37    .045       0  211.96      .1       0
Bank Sta=194.37,211.96
XS Rating Curve= 0 ,0
Exp/Cntr(USF)=0,0
Exp/Cntr=0.3,0.1

Type RM Length L Ch R = 1 ,3590    ,289.7,289.1,287.6
XS GIS Cut Line= 6
1621604.05751292502906.3140388431621634.62503709502811.091132179
1621661.63449751502724.0256895121621715.31680484502632.989126176
1621765.00961883502576.8140416741621813.58334059502503.386038929
#Sta/Elev= 30
       0  913.69    12.9  902.92    19.8  898.36    50.8  885.46    61.2  883.47
    68.1  880.43    88.7  856.61    92.2  853.74   116.3  840.21   143.7  818.74
   174.7  799.27   181.5  797.04   203.3   797.3   213.2  794.27  236.45792.4871
   245.2  791.63  252.08 792.488   258.4  796.32   271.9   808.1   276.5  813.69
     286  828.33   294.7  839.29   311.9  850.78   320.7  854.96   328.2   860.5
   346.6  871.13   361.4  883.17   388.9  896.23   424.8   906.4   459.9  922.78
#Mann= 3 ,-1,0
       0      .1       0  236.45    .045       0  252.08      .1       0
Bank Sta=236.45,252.08
XS Rating Curve= 0 ,0
Exp/Cntr(USF)=0,0
Exp/Cntr=0.3,0.1

Type RM Length L Ch R = 1 ,3301    ,300.5,300.6,297.8
XS GIS Cut Line= 6
1621833.40383901502979.3306250871621862.06093392502882.745188341
1621892.55759209502793.6252878461621937.17430076502686.625501841
1621964.35797343502616.7253791691621996.07247692502535.175345421
#Sta/Elev= 30
       0  921.72    12.1  916.78    30.8   903.7    65.1  889.44    79.3  881.64
    85.6  875.53    95.9   859.5   123.7  842.86   147.8  817.29     165  803.98
   198.5  791.24   211.1   790.4   224.8  784.68   242.6  783.92  254.13781.7297
   263.9  780.78  268.18781.7294   273.8  787.29   288.8  810.61   295.9  819.01
   317.2  840.57   329.2  850.92     352  877.91   355.9  881.07   366.5   885.3
   387.6  889.72   402.7  895.31   433.1  902.72   461.5   913.9   473.4  916.54
#Mann= 3 ,-1,0
       0      .1       0  254.13    .045       0  268.18      .1       0
Bank Sta=254.13,268.18
XS Rating Curve= 0 ,0
Exp/Cntr(USF)=0,0
Exp/Cntr=0.3,0.1

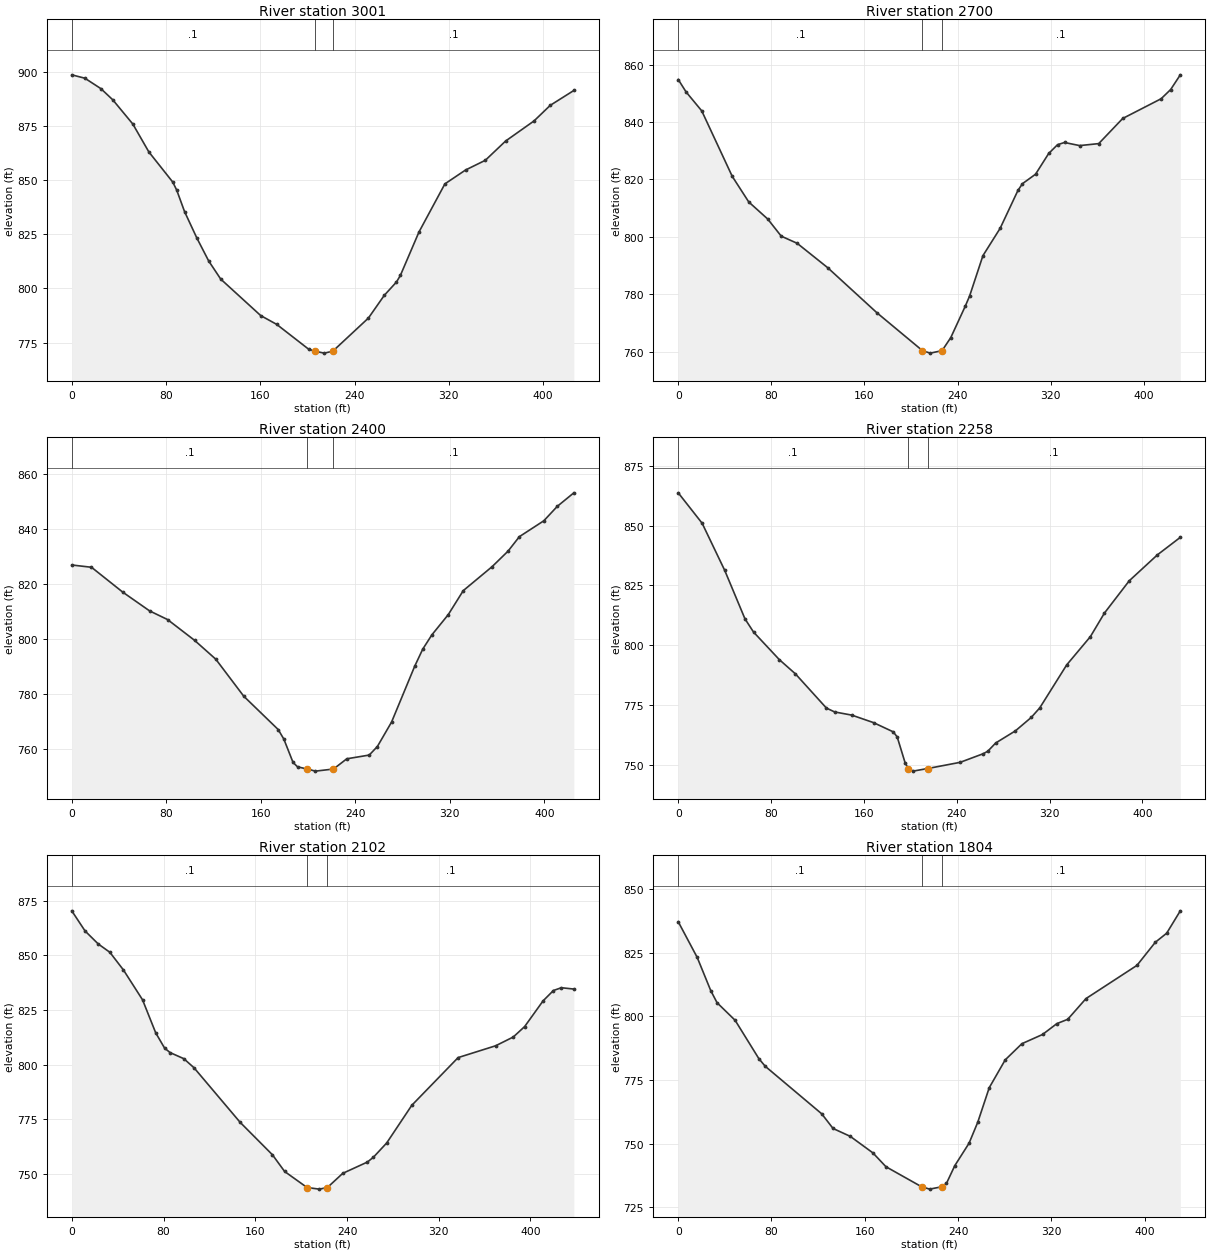
Type RM Length L Ch R = 1 ,3001    ,293.4,300.6,306.8
XS GIS Cut Line= 6
1622098.15035675503062.2120210081622120.35142784502977.575379252
1622139.38091734502905.0295925891622163.62299484502808.005508423
1622185.40215075502735.7504035831622212.00642826502651.845715761
#Sta/Elev= 30
       0  898.53    11.1  896.97    24.7  892.16    34.8     887    51.8  875.83
    65.4  862.96    85.7  849.04    89.1  845.26    95.7  835.42   106.1  823.27
   116.2  812.62   126.4  804.28   160.3  787.46   173.9  783.39   200.9  771.98
  206.09771.0243   214.3  770.13  221.48771.0229   251.7  786.31   265.2  796.82
   275.5  802.94   278.8  805.96   294.6  826.02   316.6  848.22   334.1  854.61
   350.9   859.1   368.1  867.98   392.2  877.25     406  884.46     426  891.31
#Mann= 3 ,-1,0
       0      .1       0  206.09    .045       0  221.48      .1       0
Bank Sta=206.09,221.48
XS Rating Curve= 0 ,0
Exp/Cntr(USF)=0,0
Exp/Cntr=0.3,0.1

Type RM Length L Ch R = 1 ,2700    ,303.6,300,294.6
XS GIS Cut Line= 6
1622244.79343617503108.8497230111622307.81594792503041.448939174
1622369.11897492502996.4112995861622456.08697684502947.049849749
1622521.31289625502910.0289264171622591.51485559502856.838744089
#Sta/Elev= 30
       0  854.82     6.7  850.51    20.2  843.89    46.4  821.07    60.6  812.14
    76.9   806.2    88.5  800.23   102.2  797.74   128.4  789.25   170.7  773.54
  209.87760.3318   216.5  759.47   226.7760.3312   234.2   764.9   246.7  775.89
   250.4  779.43   261.8  793.43   276.6  802.97   291.9  816.18   295.8  818.53
     307  821.81   318.3  829.04   325.9   832.1   331.9  832.87   344.9  831.79
   361.3  832.48   381.9  841.24   414.9  848.11   423.1  851.32   431.4  856.45
#Mann= 3 ,-1,0
       0      .1       0  209.87    .045       0   226.7      .1       0
Bank Sta=209.87,226.7
XS Rating Curve= 0 ,0
Exp/Cntr(USF)=0,0
Exp/Cntr=0.3,0.1

Type RM Length L Ch R = 1 ,2400    ,142.6,142,138.3
XS GIS Cut Line= 6
1622537.71082935503328.343706593 1622581.5854135503252.638477415
1622619.19262175503187.7485153381622669.33490993503101.228347167
1622706.94211817503036.3387131691622750.81670234502960.633484006
#Sta/Elev= 30
       0  826.85    16.7  826.02    43.2  816.97    65.9  810.16    81.1  807.01
   103.9  799.48   121.9  792.61   145.6  779.14   174.7  767.05   179.5  763.58
   187.3  755.09   191.1  753.49  199.25752.6804   206.3  751.92  221.53 752.681
   232.8   756.4   251.8  757.76   258.7  760.87   270.7  769.75   290.3  790.06
   297.1  796.27   304.8  801.44   318.7  808.81   331.4  817.53   355.8  826.24
   369.3  831.88   378.9  837.15   399.6  842.92     411  848.17     425  853.08
#Mann= 3 ,-1,0
       0      .1       0  199.25    .045       0  221.53      .1       0
Bank Sta=199.25,221.53
XS Rating Curve= 0 ,0
Exp/Cntr(USF)=0,0
Exp/Cntr=0.3,0.1

Type RM Length L Ch R = 1 ,2258    ,151.9,155.5,159.2
XS GIS Cut Line= 3
1622676.94699203503401.0805462021622753.68862454503253.251927787
1622823.15999713 502996.36941054
#Sta/Elev= 30
       0  863.69    20.6  850.98    40.1  831.24    57.5  811.04    64.9  805.51
    87.1     794     101  788.04   127.7  773.75   134.8  772.13   149.6   770.8
   168.3  767.67   185.3  763.81   188.7   761.7   195.5  750.92  198.23748.4928
   202.3   747.4  215.07748.4919     243  751.08     263   754.7   266.8  755.73
   273.6  759.16   290.6  764.23   304.2  769.82   311.6  773.85   334.8   791.8
   355.2   803.6   367.3  813.44   388.7  826.94     413  837.79   432.7  845.09
#Mann= 3 ,-1,0
       0      .1       0  198.23    .045       0  215.07      .1       0
Bank Sta=198.23,215.07
XS Rating Curve= 0 ,0
Exp/Cntr(USF)=0,0
Exp/Cntr=0.3,0.1

Type RM Length L Ch R = 1 ,2102    ,299.5,298.7,295.8
XS GIS Cut Line= 6
1622768.79894984503441.8772721741622815.09839793503366.844285756
1622865.99429351503311.7873092591622931.09226042503234.109971166
1622967.92059883503161.9559160021623006.02321292503077.889811173
#Sta/Elev= 30
       0  870.35    11.6  861.13    23.1  855.18    33.2  851.39    45.1  843.26
    61.7  829.65    73.2  814.52    80.9  807.58    85.7   805.5    97.7  802.71
   106.6  798.55   146.8   773.6     175  758.73   185.6  751.11  205.19743.7536
   215.8  743.03  222.88743.7548   236.3  750.25   257.8  755.42   263.1  757.66
   274.6  764.14   296.5  781.38   336.9  803.21   369.6  808.61     385  812.63
   394.9   817.4     411  829.18     420   833.9   426.9  835.17   437.8  834.56
#Mann= 3 ,-1,0
       0      .1       0  205.19    .045       0  222.88      .1       0
Bank Sta=205.19,222.88
XS Rating Curve= 0 ,0
Exp/Cntr(USF)=0,0
Exp/Cntr=0.3,0.1

Type RM Length L Ch R = 1 ,1804    ,299.5,304.1,305.4
XS GIS Cut Line= 6
1623023.68590726503549.443986177 1623087.3878796503486.905397341
1623138.36317134503429.7299867571623187.24135442 503341.38337867
1623227.45452859503277.3175619241623277.14078093503204.420398012
#Sta/Elev= 30
       0  837.23    16.3  823.18    27.9  810.16    33.3  805.41    48.8   798.5
    69.2   783.4    74.7   780.4   123.1  761.74   132.8  755.99   147.6  752.88
     167  746.39   178.2  740.95  208.75733.0817   215.7  732.15  226.17733.0817
   230.1  734.42   237.3  741.42   249.5  750.21     257  758.51   266.8  772.02
   280.5  782.95   294.8   789.3   312.5  792.92   324.8  797.19   334.1  798.88
   349.8  807.04   393.5  820.08   409.3  829.18     419  832.72   430.7  841.52
#Mann= 3 ,-1,0
       0      .1       0  208.75    .045       0  226.17      .1       0
Bank Sta=208.75,226.17
XS Rating Curve= 0 ,0
Exp/Cntr(USF)=0,0
Exp/Cntr=0.3,0.1

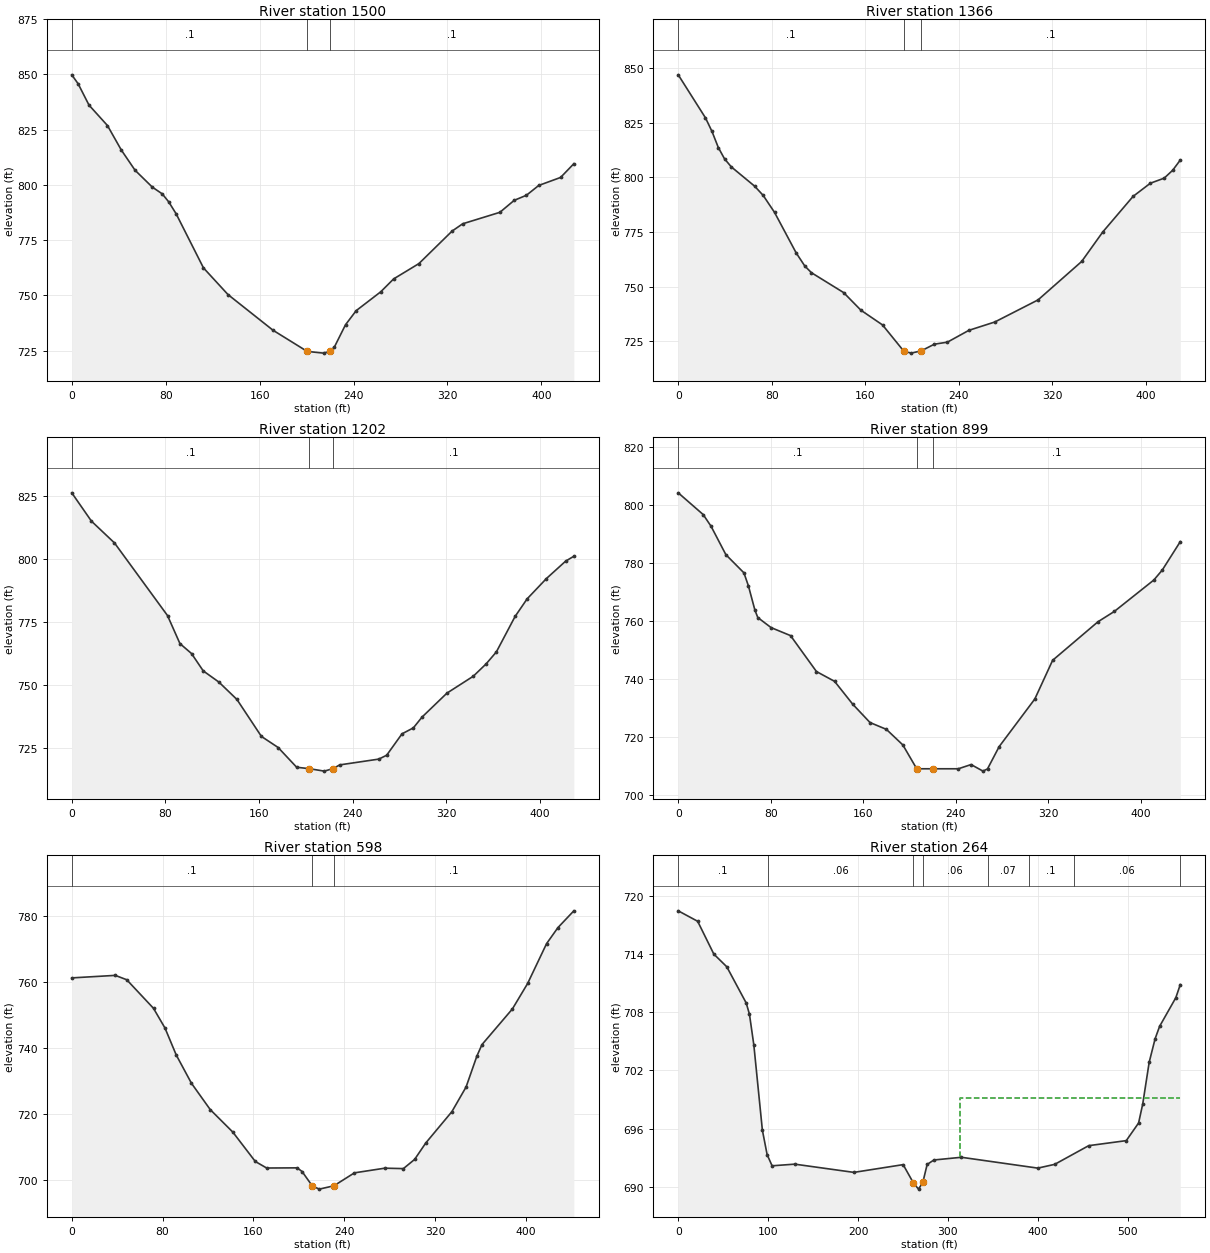
Type RM Length L Ch R = 1 ,1500    ,135.9,133.6,130.7
XS GIS Cut Line= 6
1623254.73957901503728.2231561691623310.81197342503658.780709758
1623359.41915968503600.4081230911623431.37275593503530.958130762
1623485.74764718503479.3020660881623549.18485625503419.036110505
#Sta/Elev= 30
       0  849.85     5.4  845.82    14.7  836.13    30.4   826.9    42.2  815.82
    53.9  806.68    68.6  799.04    77.1  795.97    82.6  792.35    88.9  786.97
   112.2  762.47   133.1   750.4   171.4  734.28  200.54724.6887   214.5  723.91
  219.96724.6882   223.8  726.76   233.2  736.76   242.3  743.14   263.2  751.66
   274.2   757.5   295.7  764.42     324  779.14     333  782.44   364.7  787.63
   376.9  793.05   387.3  795.35   397.8  799.79   416.4  803.41   427.7  809.63
#Mann= 3 ,-1,0
       0      .1       0  200.54    .045       0  219.96      .1       0
Bank Sta=200.54,219.96
XS Rating Curve= 0 ,0
Exp/Cntr(USF)=0,0
Exp/Cntr=0.3,0.1

Type RM Length L Ch R = 1 ,1366    ,170.4,164.5,158.3
XS GIS Cut Line= 2
1623399.93395094503833.2571082371623597.84658216503451.972365657
#Sta/Elev= 30
       0  847.01    23.3  827.31    28.9  821.06    34.3  813.71    39.6  808.55
    45.4  804.86    65.4  796.01    72.7  791.78    82.4  784.02   100.9  765.47
   108.3  759.46     114  756.39   141.5   747.3   156.3  739.23   174.8  732.48
  192.82720.5883   199.2  719.57   207.8720.5887   219.2  723.67   230.3  724.59
   248.7  730.01   270.9  733.83   307.9  743.95   345.2  761.54   363.3  775.08
   389.2  791.35     404  797.38   415.8  799.69   423.1  803.33   429.6     808
#Mann= 3 ,-1,0
       0      .1       0  192.82    .045       0   207.8      .1       0
Bank Sta=192.82,207.8
XS Rating Curve= 0 ,0
Exp/Cntr(USF)=0,0
Exp/Cntr=0.3,0.1

Type RM Length L Ch R = 1 ,1202    ,293.1,302.6,308.6
XS GIS Cut Line= 6
1623664.38836601503895.0233475121623668.63507667503805.790258259
1623657.49402285503731.409829587  1623638.278182503633.226955086
1623621.65748034503560.0916026681623627.90287468503471.046833262
#Sta/Elev= 30
       0  826.21    16.8     815    36.5  806.37    81.8  777.61    92.4  766.53
   102.3  762.59   112.3  755.72   125.6  751.32   141.1  744.41     162  729.78
   176.3  725.39   192.1  717.58  202.65 717.025   215.7  716.04  223.21717.0248
   228.9  718.51   262.3   720.8     269  722.33   282.1   730.8   291.8  733.16
   299.3  737.47   320.5  746.92     343  753.61   353.9  758.46   362.7  763.22
   378.7  777.26     389  784.24   405.5  792.29   421.9  799.17   428.9   801.1
#Mann= 3 ,-1,0
       0      .1       0  202.65    .045       0  223.21      .1       0
Bank Sta=202.65,223.21
XS Rating Curve= 0 ,0
Exp/Cntr(USF)=0,0
Exp/Cntr=0.3,0.1

Type RM Length L Ch R = 1 ,899     ,303.6,300.4,287.1
XS GIS Cut Line= 6
1623787.39599401503978.2990995941623835.25383793503905.046949506
1623876.27475326503842.2590173331623932.89045367503759.541663095
1623974.62429409503691.9299216721624020.04283842503612.067548588
#Sta/Elev= 30
       0  804.12    21.6  796.63    28.4   792.6    41.2  782.84    56.8  776.59
    60.7  772.09    66.3  763.76    68.8  761.21    80.3  757.75    97.1     755
   119.5  742.64   135.2  739.26   150.9  731.39   165.8   725.1     180  722.74
   194.2  717.39   206.2  709.19   220.1  709.19   242.2  709.19   253.2  710.64
   263.5  708.38   267.4  709.15   277.5  716.83   308.3  733.19   323.7   746.5
   362.9  759.76     377   763.3   411.2  774.12   418.5  777.55   434.1  787.34
#Mann= 3 ,-1,0
       0      .1       0   206.2    .045       0   220.1      .1       0
Bank Sta=206.2,220.1
XS Rating Curve= 0 ,0
Exp/Cntr(USF)=0,0
Exp/Cntr=0.3,0.1

Type RM Length L Ch R = 1 ,598     ,329.4,334.4,344.1
XS GIS Cut Line= 6
1624153.29552467504119.0570201721624173.48544492504029.312449008
1624164.03270793503954.3913390041624142.30670151503856.774736345
1624145.88477834503776.8828357611624164.21512225503684.089714259
#Sta/Elev= 30
       0  761.22    38.3  761.98    48.4  760.66      72  752.01    82.1  746.05
      92  737.91   105.4  729.37   121.9  721.43   141.8  714.62   161.6  705.74
   171.6  703.76   198.5  703.81   202.8   702.7  211.71698.3864   217.9  697.38
  230.83698.3857   248.9   702.3   275.6  703.71     292  703.58   301.9  706.36
   311.7  711.32   334.7  720.79   347.2  728.24   356.7  737.57   361.2  741.06
     388  751.84   401.4  759.53   418.1  771.58   428.1  776.42   442.1  781.49
#Mann= 3 ,-1,0
       0      .1       0  211.71    .045       0  230.83      .1       0
Bank Sta=211.71,230.83
XS Rating Curve= 0 ,0
Exp/Cntr(USF)=0,0
Exp/Cntr=0.3,0.1

Type RM Length L Ch R = 1 ,264     ,149.3,150.5,151.6
XS GIS Cut Line= 5
1624208.84387004504202.6530914751624380.39210229504125.255455266
1624439.11827972504025.1381664061624503.62156973  503968.8365529
1624621.63798411503848.378113908
#Sta/Elev= 30
       0  718.49    21.6  717.41    39.6  714.02      54  712.71    75.6  708.97
    79.2  707.82    84.1  704.63    93.6  695.83    98.9   693.3   104.4  692.15
   129.6  692.32   195.4  691.47   250.2  692.27   261.6  690.38   267.3  689.74
   272.1  690.44   276.9  692.29   284.4  692.75     315  693.03     400  691.91
   418.8   692.3   456.6  694.23   498.4  694.75   512.1  696.57   516.7  698.53
   523.9  702.85   530.5  705.28   535.5  706.56   553.5  709.51   558.5  710.87
#Mann= 8 ,-1,0
       0      .1       0     100     .06       0   261.6    .045       0
   272.1     .06       0  344.27     .07       0  389.89      .1       0
  439.89     .06       0  558.52      .1       0
#XS Ineff= 2 , 0
                          313.21          699.15
Permanent Ineff=
       F       F
Bank Sta=261.6,272.1
XS Rating Curve= 0 ,0
Exp/Cntr(USF)=0,0
Exp/Cntr=0.3,0.1

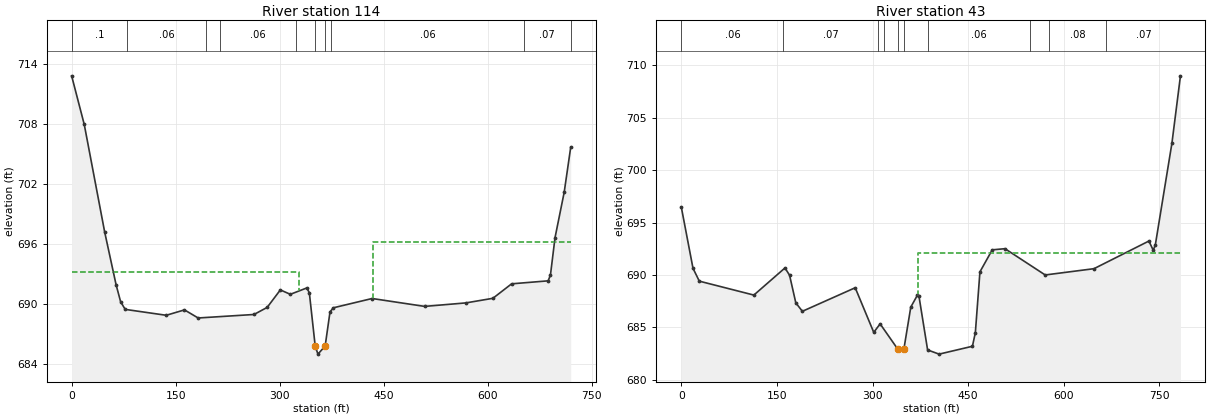
Type RM Length L Ch R = 1 ,114     ,68.6,70.2,71.4
XS GIS Cut Line= 4
1624220.25220105504289.3654679321624414.12579897504280.479594694
1624639.50385655504042.9844372391624658.89121635503845.879612685
#Sta/Elev= 30
       0  712.81    18.2  707.94    47.7  697.15    64.1  691.89    70.7  690.17
    77.3  689.42   136.4  688.83   162.7  689.37   182.4  688.56   262.9  688.91
   281.9  689.62   300.9  691.37   315.3  690.93   339.1  691.57   342.7  691.08
  351.14685.7534   355.1  684.94  365.49685.7522   372.5  689.17   377.3  689.58
   433.2  690.51   508.9  689.72   568.4  690.07   607.3  690.53   634.3  691.98
     687  692.28   690.3  692.87   696.9  696.61   710.1  701.15   719.5  705.66
#Mann= 10 ,-1,0
       0      .1       0      80     .06       0  194.08     .07       0
  214.08     .06       0  324.08     .07       0  351.14    .045       0
  365.49     .07       0  374.08     .06       0  651.49     .07       0
  719.55      .1       0
#XS Ineff= 2 , 0
          327.51  693.15  434.95          696.19
Permanent Ineff=
       F       F
Bank Sta=351.14,365.49
XS Rating Curve= 0 ,0
Exp/Cntr(USF)=0,0
Exp/Cntr=0.3,0.1

Type RM Length L Ch R = 1 ,43      ,,,
XS GIS Cut Line= 5
 1624252.9683707504331.7753174781624440.28096294504316.291279457
1624581.65924519504206.898909636 1624647.1780198504145.171979478
1624699.20753971503822.928140288
#Sta/Elev= 30
       0  696.46    18.3  690.63    28.2   689.4   113.8  688.07   162.6  690.66
   169.8  689.97   179.6  687.33   189.9  686.52   272.8  688.77   301.9  684.51
   311.9  685.32   339.2  682.94   349.3  682.96     360  686.92   370.3  688.05
   372.9  687.94   386.4  682.83   404.4  682.43   456.7  683.18   461.3  684.48
   468.5  690.29   487.8  692.39   507.8   692.5   570.9  689.99   647.4  690.59
   733.6  693.23   740.4  692.35   743.7  692.87   769.7  702.57   783.1  709.01
#Mann= 10 ,-1,0
       0     .06       0     160     .07       0  307.95     .06       0
  317.95     .07       0   339.2    .045       0   349.3     .07       0
  386.71     .06       0  546.73     .07       0  576.73     .08       0
  666.73     .07       0
#XS Ineff= 2 , 0
                          371.99          692.08
Permanent Ineff=
       F       F
Bank Sta=339.2,349.3
XS Rating Curve= 0 ,0
Exp/Cntr(USF)=0,0
Exp/Cntr=0.3,0.1
LCMann Table=0

Chan Stop Cuts=-1
Use User Specified Reach Order=0
Composite Channel Slope=5